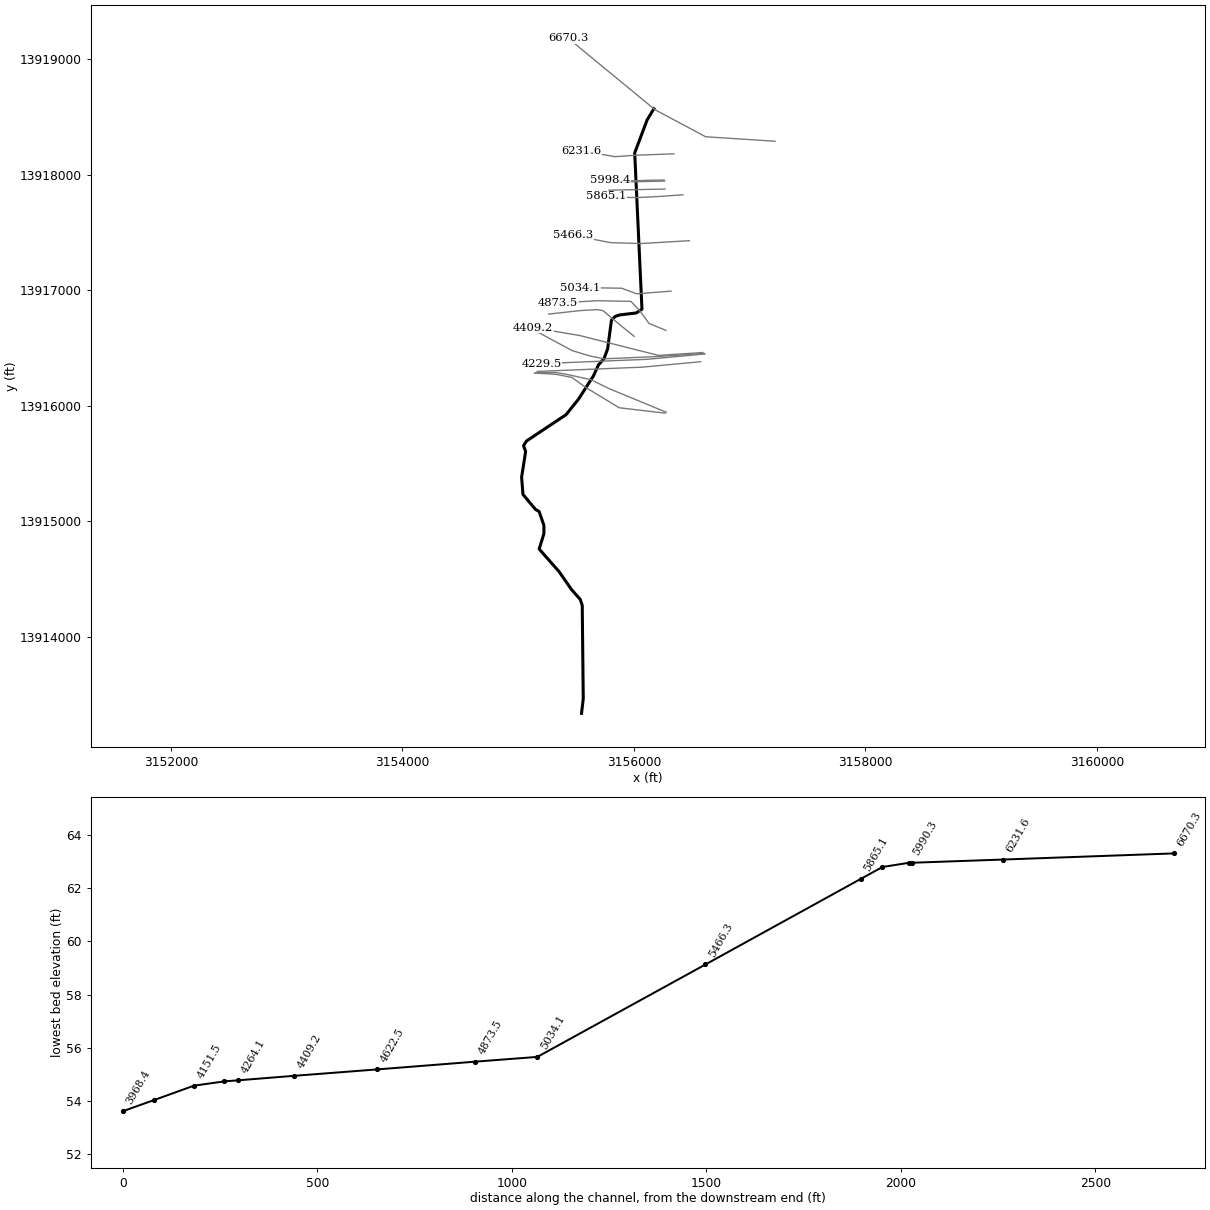
--- P130-03-00.PRJ (project) ---

Proj Title=P130-03-00
Current Plan=p02
Default Exp/Contr=.3,.1
English Units
Geom File=g01
Flow File=f01
Flow File=f02
Plan File=p01
Plan File=p02
Y Axis Title=Elevation
X Axis Title(PF)=Main Channel Distance
X Axis Title(XS)=Station
BEGIN DESCRIPTION:
Greens Bayou Watershed
Tributary 3.19 to Garners Bayou
HCFCD Unit P130-03-00
Flood Hazard Model
10, 2, 1, 0.2% Event
Filename P130-03-00.prj
Prepared by:  Watershed Concepts  Date:
Reviewed by:                      Date:
STATUS FINAL
END DESCRIPTION:
DSS Export Rating Curves= 0
DSS Export Rating Curve Sorted= 0
DSS Export Volume Flow Curves= 0
DXF OffsetX= 0
DXF OffsetY= 0
DXF ScaleX= 1
DXF ScaleY= 10

--- P130-03-00.p02 (plan) ---

Plan Title=Floodway
Version=Version 3.0.1  Mar 2001
Short Identifier=Floodway0607
Geom File=g01
Flow File=f02
Subcritical Flow
K Sum by GR= 0
Std Step Tol= 0.01
Critical Tol= 0.01
Num of Std Step Trials= 20
Max Error Tol= 0.3
Flow Tol Ratio= 0.001
Split Flow NTrial= 30
Split Flow Tol= 0.02
Split Flow Ratio= 0.02
Log Output Level= 0
Friction Slope Method= 1
Unsteady Friction Slope Method= 2
Parabolic Critical Depth
Global Vel Dist= 0 , 0 , 0
Global Log Level= 0
CheckData=True
Encroach Param=-1 ,0,0, 2
Encroach River=P130-03-00
Encroach Reach=Reach - 1
Encroach Node=6670.3
       1    4950    5050
Encroach Node=6231.6
       1    4910    5160
Encroach Node=5998.4
       1    4910    5150
Encroach Node=5990.3
       1    4925    5136
Encroach Node=5955.8
       1    4925    5136
Encroach Node=5921.3
       1    4925    5136
Encroach Node=5865.1
       1    4925    5136
Encroach Node=5466.3
       1    4912    5136
Encroach Node=5034.1
       1    4970    5140
Encroach Node=4873.5
       1    4938    5050
Encroach Node=4622.5
       1    4910    5090
Encroach Node=4409.2
       1    4860    5140
Encroach Node=4264.1
       1    4920    5100
Encroach Node=4229.5
       1    4952    5090
Encroach Node=4190.5
       1    4952    5090
Encroach Node=4151.5
       1    4952    5090
Encroach Node=4049.1
       1    4906    5060
Encroach Node=3968.4
       1    4920    5050
Encroach Node=3734.2
       1    4920    5080
Encroach Node=3222.6
       1    4870  5030.7
Encroach Node=2975.5
       1    4930  5030.7
Encroach Node=2710.2
       1    4900    5100
Encroach Node=2537.0
       1    4890    5110
Encroach Node=2462.9
       1    4880    5060
Encroach Node=2440.9
       1    4880    5120
Encroach Node=2418.9
       1    4880    5120
Encroach Node=2375.7
       1    4880    5120
Encroach Node=2088.9
       1    4840    5060
Encroach Node=1695.9
       1  4974.7  5026.6
Encroach Node=747.1
       1  4975.2  5034.4
Encroach Reach=P130-03-00_0007
Encroach Node=6670.3
       1    4950    5050
Encroach Node=6231.6
       1    4910    5160
Encroach Node=5998.4
       1    4910    5150
Encroach Node=5990.3
       1    4925    5136
Encroach Node=5955.8
       1    4925    5136
Encroach Node=5921.3
       1    4925    5136
Encroach Node=5865.1
       1    4925    5136
Encroach Node=5466.3
       1    4912    5136
Encroach Node=5034.1
       1    4970    5140
Encroach Node=4873.5
       1    4938    5050
Encroach Node=4622.5
       1    4910    5090
Encroach Node=4409.2
       1    4860    5140
Encroach Node=4264.1
       1    4920    5100
Encroach Node=4229.5
       1    4952    5090
Encroach Node=4190.5
       1    4952    5090
Encroach Node=4151.5
       1    4952    5090
Encroach Node=4049.1
       1    4906    5060
Encroach Node=3968.4
       1    4920    5050
Encroach Node=3734.2
       1    4920    5080
Encroach Node=3222.6
       1    4870  5030.7
Encroach Node=2975.5
       1    4930  5030.7
Encroach Node=2710.2
       1    4900    5100
Encroach Node=2537.0
       1    4890    5110
Encroach Node=2462.9
       1    4880    5060
Encroach Node=2440.9
       1    4880    5120
Encroach Node=2418.9
       1    4880    5120
Encroach Node=2375.7
       1    4880    5120
Encroach Node=2088.9
       1    4840    5060
Encroach Node=1695.9
       1  4974.7  5026.6
Encroach Node=747.1
       1  4975.2  5034.4
Computation Interval=1HOUR
Output Interval=1HOUR
Run HTab= 0
Run UNet= 0
Run PostProcess= 0
UNET Theta= 1
UNET ZTol= 0.02
UNET ZSATol= 0.1
UNET MxIter= 20
UNET MaxInSteps= 20
UNET DtIC= 0
UNET DtMin= 0
UNET MaxCRTS= 20
UNET WFStab= 2
UNET SFStab= 1
UNET WFX= 1
UNET SFX= 1
UNET Convert EG Bridges=-1
UNET Use Existing IB Tables=-1
Instantaneous Interval=1HOUR
Write IC File= 0
Write Velocity= 0
Write Detailed= 0

--- P130-03-00.p01 (plan) ---

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Plan Title=FEMA Effective June 2007
Short Identifier=FEMAeff0607
Geom File= g01
Flow File= f01
Interactive Comp Mode
Encroach Param= -1, 0, 0, 0

--- P130-03-00.f02 (steady flow) ---

Flow Title= Floodway
Number of Profiles= 2
Profile Names=1PCT_100yr, 1PCTFloodway_100yrFW
River Rch & RM=P130-03-00,P130-03-00_0007,6670.3
     986     986
River Rch & RM=P130-03-00,P130-03-00_0007,6231.6
    1013    1013
River Rch & RM=P130-03-00,P130-03-00_0007,5865.1
    1044    1044
River Rch & RM=P130-03-00,P130-03-00_0007,5466.3
    1078    1078
River Rch & RM=P130-03-00,P130-03-00_0007,5034.1
    1130    1130
River Rch & RM=P130-03-00,P130-03-00_0007,4409.2
    1145    1145
River Rch & RM=P130-03-00,P130-03-00_0007,4229.5
    1188    1188
River Rch & RM=P130-03-00,P130-03-00_0007,3734.2
    1234    1234
River Rch & RM=P130-03-00,P130-03-00_0007,3222.6
    1861    1861
Boundary for River Rch & Prof#=P130-03-00,P130-03-00_0007, 1
Up Type= 0
Dn Type= 3
Dn Slope= 0.00200
Boundary for River Rch & Prof#=P130-03-00,P130-03-00_0007, 2
Up Type= 0
Dn Type= 1
Dn Known WS=57.70

--- P130-03-00.f01 (steady flow) ---

Flow Title= FEMA Effective June 2007
Program Version=3.11
Number of Profiles= 4
Profile Names=10PCT_10yr, 2PCT_50yr, 1PCT_100yr, 0.2PCT_500yr
River Rch & RM=P130-03-00,P130-03-00_0007 ,6670.3
     580     849     986    1374
River Rch & RM=P130-03-00,P130-03-00_0007 ,6231.6
     596     872    1013    1413
River Rch & RM=P130-03-00,P130-03-00_0007 ,5865.1
     614     899    1044    1455
River Rch & RM=P130-03-00,P130-03-00_0007 ,5466.3
     634     928    1078    1503
River Rch & RM=P130-03-00,P130-03-00_0007 ,5034.1
     664     973    1130    1574
River Rch & RM=P130-03-00,P130-03-00_0007 ,4409.2
     673     986    1145    1596
River Rch & RM=P130-03-00,P130-03-00_0007 ,4229.5
     699    1023    1188    1656
River Rch & RM=P130-03-00,P130-03-00_0007 ,3734.2
     726    1062    1234    1720
River Rch & RM=P130-03-00,P130-03-00_0007 ,3222.6
    1093    1602    1861    2595
Boundary for River Rch & Prof#=P130-03-00,P130-03-00_0007 , 1
Up Type= 0
Dn Type= 3
Dn Slope=0.002
Boundary for River Rch & Prof#=P130-03-00,P130-03-00_0007 , 2
Up Type= 0
Dn Type= 3
Dn Slope=0.002
Boundary for River Rch & Prof#=P130-03-00,P130-03-00_0007 , 3
Up Type= 0
Dn Type= 3
Dn Slope=0.002
Boundary for River Rch & Prof#=P130-03-00,P130-03-00_0007 , 4
Up Type= 0
Dn Type= 3
Dn Slope=0.002
DSS Import GetInterval= 0
DSS Import GetPeak= 0
DSS Import FillOption= 0

--- P130-03-00.g01 (geometry) ---

Geom Title=P130-03-00 June 2007
Version=Version 3.0.1  Mar 2001

River Reach=P130-03-00      ,P130-03-00_0007
Reach XY= 30
      3156172.93     13918571.46       3156114.5       13918475.
      3156007.25       13918189.        3156070.       13916836.
      3156020.75       13916804.       3155873.5       13916786.
      3155837.75       13916773.       3155806.5       13916742.
       3155773.5       13916493.       3155741.5       13916407.
      3155694.75       13916355.      3155650.25       13916258.
      3155520.75       13916056.        3155414.       13915923.
      3155072.25       13915695.      3155046.75       13915654.
        3155065.       13915605.      3155030.29     13915382.24
      3155041.75       13915233.      3155149.25       13915104.
      3155181.75       13915084.      3155222.75       13914965.
      3155222.75       13914892.      3155181.75       13914760.
      3155354.75       13914563.        3155462.       13914408.
       3155536.5       13914324.        3155554.       13914272.
      3155562.75       13913464.      3155547.75       13913337.

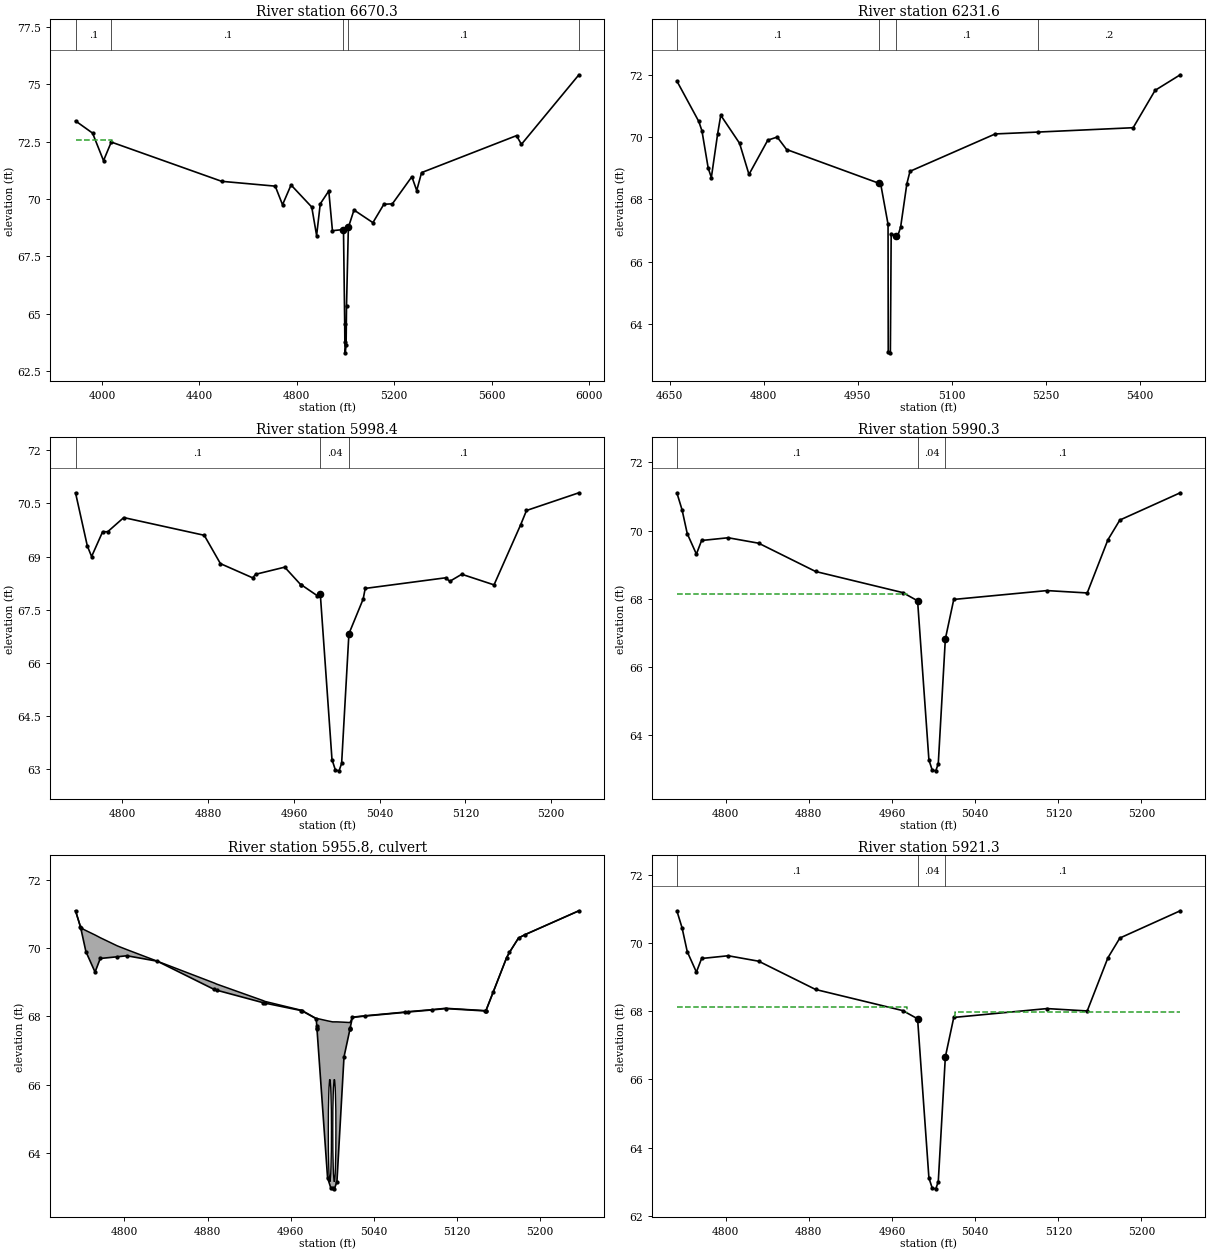
Type RM Length L Ch R = 1 ,6670.3  ,417.5,438.7,558
BEGIN DESCRIPTION:
Cross Section 6670.3
END DESCRIPTION:
XS GIS Cut Line= 4
      3157219.04     13918290.51      3156620.05     13918329.23
      3156182.61     13918563.45      3155433.23     13919181.36
#Sta/Elev= 30
    3891    73.4    3961   72.87    4006   71.67  4037.8   72.48  4491.3   70.77
  4711.3   70.56  4741.3   69.75  4776.3   70.61  4861.3   69.65  4881.3   68.41
  4896.3   69.79  4931.3   70.35  4946.3   68.62  4991.7   68.67  4996.7   64.56
  4997.3   63.77  4998.9    63.3  5002.5   63.64  5004.1   65.32  5011.7   68.76
  5034.8   69.52  5112.5   68.97  5157.5   69.77  5192.5   69.79  5272.5   70.97
  5292.5   70.37  5312.5   71.15  5702.5   72.76  5722.5   72.38  5958.7   75.41
#Mann= 5 , 1 , 0
    3891      .1       0  4037.8      .1       0  4991.7     .04       0
  5011.7      .1       0  5958.7      .2       0
#XS Ineff= 2 , 0
       0    4041   72.56               0
Permanent Ineff=
       F       F
Bank Sta=4991.7,5011.7
XS Rating Curve= 0
Exp/Cntr=.3,.1

Type RM Length L Ch R = 1 ,6231.6  ,233.9,233.2,246.9
BEGIN DESCRIPTION:
Cross Section 6231.6 - Interpolated
END DESCRIPTION:
XS GIS Cut Line= 4
      3156346.35      13918181.6      3156009.73     13918169.13
      3155839.35     13918156.66      3155548.44     13918206.53
#Sta/Elev= 28
  4661.6    71.8  4696.6    70.5  4701.6    70.2  4711.6      69  4716.6    68.7
  4726.6    70.1  4731.6    70.7  4761.6    69.8  4776.6    68.8  4806.6    69.9
  4821.6      70  4836.6    69.6  4984.6   68.51  4986.6    68.5  4998.4    67.2
  4998.7   63.09  5002.1   63.07  5003.4    66.9  5011.3   66.82  5013.4    66.8
  5018.4    67.1  5028.4    68.5  5033.4    68.9  5169.3    70.1  5237.3   70.16
  5389.3    70.3  5424.3    71.5  5464.4      72
#Mann= 4 , 1 , 0
  4661.6      .1       0  4984.6     .04       0  5011.3      .1       0
  5237.3      .2       0
#XS Ineff= 2 , 0
       0  4731.6    70.7               0
Permanent Ineff=
       F       F
Bank Sta=4984.6,5011.3
XS Rating Curve= 0
Exp/Cntr=.3,.1

Type RM Length L Ch R = 1 ,5998.4  ,3.5,8.1,4.1
BEGIN DESCRIPTION:
Cross Section 5998.4 - Interpolated
END DESCRIPTION:
XS GIS Cut Line= 6
       3156262.2     13917954.38      3156124.09      13917952.5
      3156019.11      13917948.3      3155906.78      13917946.2
      3155847.99     13917949.35      3155793.05     13917955.58
#Sta/Elev= 29
  4756.2    70.8  4767.2    69.3  4771.2      69  4781.5    69.7  4786.2    69.7
  4801.2    70.1  4876.3    69.6  4891.4    68.8  4921.4    68.4  4924.4    68.5
  4951.4    68.7  4966.5    68.2    4967    68.2  4981.5    67.9  4984.6   67.94
  4995.5   63.27  4998.7   62.97  5002.1   62.95  5004.5   63.16  5011.3   66.82
  5024.6    67.8  5026.5    68.1  5101.6    68.4  5105.4    68.3  5116.6    68.5
  5146.7    68.2  5171.6    69.9    5177    70.3  5225.9    70.8
#Mann= 3 , 1 , 0
  4756.2      .1       0  4984.6     .04       0  5011.3      .1       0
#XS Ineff= 2 , 0
       0  4801.2    70.1               0
Permanent Ineff=
       F       F
Bank Sta=4984.6,5011.3
XS Rating Curve= 0
Exp/Cntr=.5,.3

Type RM Length L Ch R = 1 ,5990.3  ,69,69,69
BEGIN DESCRIPTION:
Upstream Section of Bridge/Culvert/Weir
END DESCRIPTION:
XS GIS Cut Line= 2
      3156265.67     13917945.27      3155781.46     13917935.54
#Sta/Elev= 21
    4753   71.11    4758   70.61    4763   69.91  4771.8   69.31  4776.8   69.71
  4802.4   69.79  4831.7   69.63  4886.5    68.8  4970.4   68.18  4984.6   67.94
  4995.5   63.27  4998.7   62.97  5002.1   62.95  5004.5   63.16  5011.3   66.82
  5019.4   67.98  5109.1   68.24  5147.8   68.17  5167.7   69.73  5179.2   70.31
  5237.3   71.11
#Mann= 3 , 1 , 0
    4753      .1       0  4984.6     .04       0  5011.3      .1       0
#XS Ineff= 2 , 0
       0    4974   68.13    5021       0   67.97
Permanent Ineff=
       F       F
Bank Sta=4984.6,5011.3
XS Rating Curve= 0
Exp/Cntr=.5,.3

Type RM Length L Ch R = 2 ,5955.8  ,,,
BEGIN DESCRIPTION:
MEADOW BROOK
Structure ID: P03-3
END DESCRIPTION:
Bridge Culvert--1,0,-1,-1, 0
Deck Dist Width WeirC Skew NumUp NumDn MinLoCord MaxHiCord MaxSubmerge Is_Ogee
10,49,3,0, 43, 43, , , .95, 0, 1,1,,
    4753  4757.7    4758    4763  4771.8  4776.8  4793.2  4802.4  4831.7  4886.5
  4888.7  4933.8  4935.3  4970.4  4971.1  4984.6 4985.09  4985.2 4985.31  4995.5
  4998.7  5000.4  5002.1  5004.5  5011.3 5016.99  5017.1 5017.21  5019.4  5031.6
  5070.4  5073.1  5096.1  5109.1  5147.3  5147.7  5147.8  5155.1  5167.7  5170.5
  5179.2  5185.5  5237.3
    71.1   70.64    70.6   70.52   70.39   70.31   70.07   69.96   69.62   68.98
   68.95   68.46   68.44   68.18   68.17   67.94   67.94   67.94   67.94   67.87
   67.85   67.84   67.84   67.84   67.83   67.82   67.82   67.82   67.98   68.02
   68.13   68.14    68.2   68.24   68.17   68.17   68.17   68.74   69.72   69.88
    70.3    70.4    71.1
    71.1   70.63    70.6    69.9    69.3    69.7   69.75   69.78   69.62   68.79
   68.77    68.4   68.39   68.17   68.16   67.93   67.72   67.67   67.63   63.26
   62.96   62.95   62.94   63.15   66.81   67.62   67.64   67.66   67.97   68.01
   68.12   68.13   68.19   68.23   68.16   68.16   68.16   68.73   69.72   69.88
    70.3    70.4    71.1
    4753  4757.7    4758    4763  4771.8  4776.8  4793.2  4802.4  4831.7  4886.5
  4888.7  4933.8  4935.3  4970.4  4971.1  4984.6 4985.09  4985.2 4985.31  4995.5
  4998.7  5000.4  5002.1  5004.5  5011.3 5016.99  5017.1 5017.21  5019.4  5031.6
  5070.4  5073.1  5096.1  5109.1  5147.3  5147.7  5147.8  5155.1  5167.7  5170.5
  5179.2  5185.5  5237.3
    71.1   70.64    70.6   70.52   70.39   70.31   70.07   69.96   69.62   68.98
   68.95   68.46   68.44   68.18   68.17   67.94   67.94   67.94   67.94   67.87
   67.85   67.84   67.84   67.84   67.83   67.82   67.82   67.82   67.98   68.02
   68.13   68.14    68.2   68.24   68.17   68.17   68.17   68.74   69.72   69.88
    70.3    70.4    71.1
   71.03   70.56   70.53   69.83   69.23   69.63   69.68   69.71   69.55   68.72
    68.7   68.33   68.32    68.1   68.09   67.86   67.65    67.6   67.56   63.19
   62.89   62.88   62.87   63.08   66.74   67.55   67.57   67.59    67.9   67.94
   68.05   68.06   68.12   68.16   68.09   68.09   68.09   68.66   69.65   69.81
   70.23   70.33   71.03
BR Coef= 1 , 0 , 0 ,1.25, 0 ,,,.8,-1,2,0,
WSPro=,,,, 1 ,,,, 0 ,,,, 0 ,,,,-1 ,-1 ,-1 , 0 , 0 , 0 , 0 , 0
Culvert=1,3,,49,.015,.2,1,1,2,63.15,4997.7,62.82,4997.7,Culvert #1  , 0 ,10
Culvert Bottom n=.015
Culvert=1,3,,49,.015,.2,1,1,2,63.15,5002,62.82,5002,Culvert #2  , 0 ,10
Culvert Bottom n=.015
BR U #Sta/Elev= 43
    4753    71.1  4757.7   70.63    4758    70.6    4763    69.9  4771.8    69.3
  4776.8    69.7  4793.2   69.75  4802.4   69.78  4831.7   69.62  4886.5   68.79
  4888.7   68.77  4933.8    68.4  4935.3   68.39  4970.4   68.17  4971.1   68.16
  4984.6   67.93 4985.09   67.72  4985.2   67.67 4985.31   67.63  4995.5   63.26
  4998.7   62.96  5000.4   62.95  5002.1   62.94  5004.5   63.15  5011.3   66.81
 5016.99   67.62  5017.1   67.64 5017.21   67.66  5019.4   67.97  5031.6   68.01
  5070.4   68.12  5073.1   68.13  5096.1   68.19  5109.1   68.23  5147.3   68.16
  5147.7   68.16  5147.8   68.16  5155.1   68.73  5167.7   69.72  5170.5   69.88
  5179.2    70.3  5185.5    70.4  5237.3    71.1
BR U #Mann= 3
    4753      .1  4984.6     .04  5011.3      .1
BR U Banks=4984.6,5011.3
BR D #Sta/Elev= 43
    4753   71.03  4757.7   70.56    4758   70.53    4763   69.83  4771.8   69.23
  4776.8   69.63  4793.2   69.68  4802.4   69.71  4831.7   69.55  4886.5   68.72
  4888.7    68.7  4933.8   68.33  4935.3   68.32  4970.4    68.1  4971.1   68.09
  4984.6   67.86 4985.09   67.65  4985.2    67.6 4985.31   67.56  4995.5   63.19
  4998.7   62.89  5000.4   62.88  5002.1   62.87  5004.5   63.08  5011.3   66.74
 5016.99   67.55  5017.1   67.57 5017.21   67.59  5019.4    67.9  5031.6   67.94
  5070.4   68.05  5073.1   68.06  5096.1   68.12  5109.1   68.16  5147.3   68.09
  5147.7   68.09  5147.8   68.09  5155.1   68.66  5167.7   69.65  5170.5   69.81
  5179.2   70.23  5185.5   70.33  5237.3   71.03
BR D #Mann= 3
    4753      .1  4984.6     .04  5011.3      .1
BR D Banks=4984.6,5011.3
BC Design=,, 0 ,, 0 ,,,,,,

Type RM Length L Ch R = 1 ,5921.3  ,56.2,56.2,56.2
BEGIN DESCRIPTION:
Downstream Section of Bridge/Culvert/Weir
END DESCRIPTION:
XS GIS Cut Line= 2
      3156269.31     13917876.37       3155785.1     13917866.64
#Sta/Elev= 21
    4753   70.95    4758   70.45    4763   69.75  4771.8   69.15  4776.8   69.55
  4802.4   69.63  4831.7   69.47  4886.5   68.64  4970.4   68.02  4984.6   67.78
  4995.5   63.11  4998.7   62.81  5002.1   62.79  5004.5      63  5011.3   66.66
  5019.4   67.82  5109.1   68.08  5147.8   68.01  5167.7   69.57  5179.2   70.15
  5237.3   70.95
#Mann= 3 , 1 , 0
    4753      .1       0  4984.6     .04       0  5011.3      .1       0
#XS Ineff= 2 , 0
       0    4974   68.13    5021       0   67.97
Permanent Ineff=
       F       F
Bank Sta=4984.6,5011.3
XS Rating Curve= 0
Exp/Cntr=.5,.3

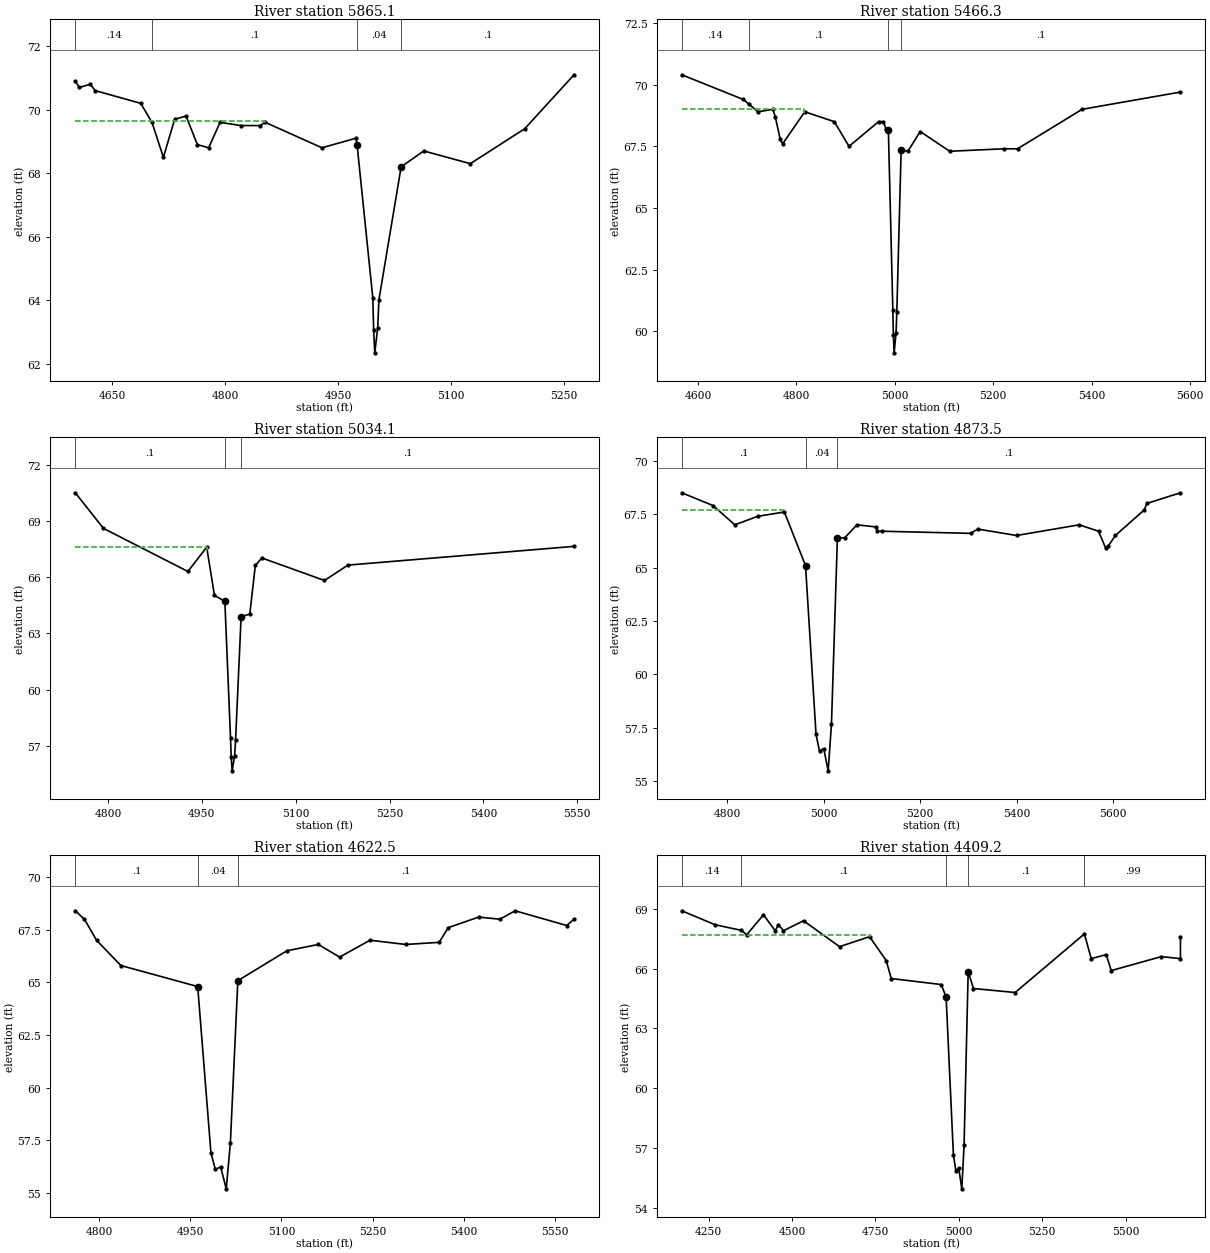
Type RM Length L Ch R = 1 ,5865.1  ,406,398.8,395.9
BEGIN DESCRIPTION:
Cross Section 5865.1 - Interpolated
END DESCRIPTION:
XS GIS Cut Line= 5
      3156424.11     13917826.74      3156204.43      13917811.5
      3156029.57     13917802.99      3155828.41     13917805.13
      3155763.56     13917813.53
#Sta/Elev= 28
  4601.1    70.9  4606.6    70.7  4620.7    70.8  4627.8    70.6  4687.9    70.2
  4702.9    69.6    4718    68.5    4733    69.7  4748.1    69.8  4763.1    68.9
  4778.1    68.8  4793.2    69.6  4821.3    69.5  4846.1    69.5  4853.3    69.6
  4928.4    68.8  4973.4    69.1    4975    68.9  4995.9   64.07    4997   63.07
  4998.5   62.34  5002.4   63.13    5004   64.01  5033.5    68.2  5063.5    68.7
  5125.3    68.3  5197.5    69.4  5262.9    71.1
#Mann= 4 , 1 , 0
  4601.1     .14       0  4702.9      .1       0    4975     .04       0
  5033.5      .1       0
#XS Ineff= 2 , 0
       0    4853   69.65               0
Permanent Ineff=
       F       F
Bank Sta=4975,5033.5
XS Rating Curve= 0
Exp/Cntr=.3,.1

Type RM Length L Ch R = 1 ,5466.3  ,430.4,432.2,460.3
BEGIN DESCRIPTION:
Cross Section 5466.3 - Interpolated
END DESCRIPTION:
XS GIS Cut Line= 5
      3156479.34      13917429.4      3156055.45     13917404.47
      3155797.79     13917412.78      3155668.96     13917437.71
      3155474.15     13917482.67
#Sta/Elev= 28
  4566.9    70.4  4691.9    69.4  4702.9   69.22  4721.9    68.9  4751.9      69
  4756.9    68.7  4766.9    67.8  4771.9    67.6  4816.9    68.9  4876.9    68.5
  4906.9    67.5  4966.9    68.5  4976.9    68.5  4981.9    68.2  4986.8   68.18
  4995.9   60.86    4997   59.86  4998.5   59.13  5002.4   59.92    5004    60.8
  5012.8   67.35  5026.5    67.3  5051.5    68.1  5111.5    67.3  5221.5    67.4
  5249.3    67.4  5380.5      69  5580.5    69.7
#Mann= 4 , 1 , 0
  4566.9     .14       0  4702.9      .1       0  4986.8     .04       0
  5012.8      .1       0
#XS Ineff= 2 , 0
       0    4815      69               0
Permanent Ineff=
       F       F
Bank Sta=4986.8,5012.8
XS Rating Curve= 0
Exp/Cntr=.3,.1

Type RM Length L Ch R = 1 ,5034.1  ,226.5,160.6,63.6
BEGIN DESCRIPTION:
Cross Section 5034.1
END DESCRIPTION:
XS GIS Cut Line= 5
      3156321.26     13916992.55      3156064.28     13916972.68
      3156023.95     13916969.68      3155895.05     13917017.76
      3155533.77     13917023.52
#Sta/Elev= 18
  4747.8    70.5  4792.8    68.6  4927.8    66.3  4957.8    67.6  4970.2   65.02
  4986.8   64.71  4995.9   57.39    4997   56.39  4998.5   55.66  5002.4   56.45
    5004   57.33  5012.8   63.88  5026.7   64.03  5035.5   66.62    5046   67.02
    5146   65.82  5183.5   66.64  5544.8   67.64
#Mann= 3 , 1 , 0
  4747.8      .1       0  4986.8     .04       0  5012.8      .1       0
#XS Ineff= 2 , 0
       0    4959    67.6               0
Permanent Ineff=
       F       F
Bank Sta=4986.8,5012.8
XS Rating Curve= 0
Exp/Cntr=.3,.1

Type RM Length L Ch R = 1 ,4873.5  ,227.7,251,157.5
BEGIN DESCRIPTION:
Cross Section 4873.5 - Interpolated
END DESCRIPTION:
XS GIS Cut Line= 6
      3156276.88     13916652.75      3156130.97     13916712.82
      3156051.47     13916822.47      3155974.72     13916904.02
      3155685.58     13916909.93      3155346.19     13916889.96
#Sta/Elev= 28
  4705.5    68.5  4770.5    67.9  4815.5      67  4863.3    67.4  4918.3    67.6
  4962.2   65.09    4984   57.19  4991.2    56.4    5000   56.52  5009.2   55.48
    5016   57.66  5028.3   66.37  5043.8    66.4  5068.8      67  5108.8    66.9
  5110.7    66.7  5120.7    66.7  5304.6    66.6  5319.6    66.8  5399.9    66.5
  5529.9      67  5569.9    66.7  5584.9    65.9  5589.9      66  5604.9    66.5
  5664.9    67.7  5669.9      68  5739.9    68.5
#Mann= 3 , 1 , 0
  4705.5      .1       0  4962.2     .04       0  5028.3      .1       0
#XS Ineff= 2 , 0
       0    4918    67.7               0
Permanent Ineff=
       F       F
Bank Sta=4962.2,5028.3
XS Rating Curve= 0
Exp/Cntr=.3,.1

Type RM Length L Ch R = 1 ,4622.5  ,187.6,213.3,256.1
BEGIN DESCRIPTION:
Cross Section 4622.5 - Interpolated
END DESCRIPTION:
XS GIS Cut Line= 6
      3156002.42      13916601.1      3155822.72     13916747.85
       3155734.1     13916823.34      3155683.17     13916832.45
      3155539.49     13916824.51      3155264.16     13916794.05
#Sta/Elev= 23
  4760.7    68.4  4775.7      68  4795.7      67  4835.7    65.8  4962.2    64.8
    4984    56.9  4991.2   56.11    5000   56.23  5009.2   55.19    5016   57.37
  5028.3   65.08  5109.1    66.5  5160.8    66.8  5195.8    66.2  5245.8      67
  5304.7    66.8  5359.7    66.9  5374.7    67.6  5424.7    68.1  5459.7      68
  5484.7    68.4  5569.7    67.7  5581.7      68
#Mann= 3 , 1 , 0
  4760.7      .1       0  4962.2     .04       0  5028.3      .1       0
Bank Sta=4962.2,5028.3
XS Rating Curve= 0
Exp/Cntr=.3,.1

Type RM Length L Ch R = 1 ,4409.2  ,98.5,145.1,149.9
BEGIN DESCRIPTION:
Cross Section 4409.2 - Interpolated
END DESCRIPTION:
XS GIS Cut Line= 5
       3156595.7      13916461.1      3156213.37     13916436.17
      3155785.32     13916544.22      3155540.13     13916606.56
      3155128.71      13916677.2
#Sta/Elev= 30
  4169.6    68.9  4269.6    68.2  4347.8   67.92  4364.6    67.7  4414.6    68.7
  4449.6    67.9  4459.6    68.2  4474.6    67.9  4534.6    68.4  4642.7    67.1
  4732.7    67.6  4782.7    66.4  4797.7    65.5  4947.7    65.2  4962.2   64.56
    4984   56.66  4991.2   55.87    5000   55.99  5009.2   54.95    5016   57.13
  5028.3   65.84  5044.2      65  5169.2    64.8  5376.8   67.74  5397.2    66.5
  5442.2    66.7  5457.2    65.9  5607.2    66.6  5664.7    66.5  5664.8    67.6
#Mann= 5 , 1 , 0
  4169.6     .14       0  4347.8      .1       0  4962.2     .04       0
  5028.3      .1       0  5376.8     .99       0
#XS Ineff= 2 , 0
       0    4734    67.7               0
Permanent Ineff=
       F       F
Bank Sta=4962.2,5028.3
XS Rating Curve= 0
Exp/Cntr=.3,.1

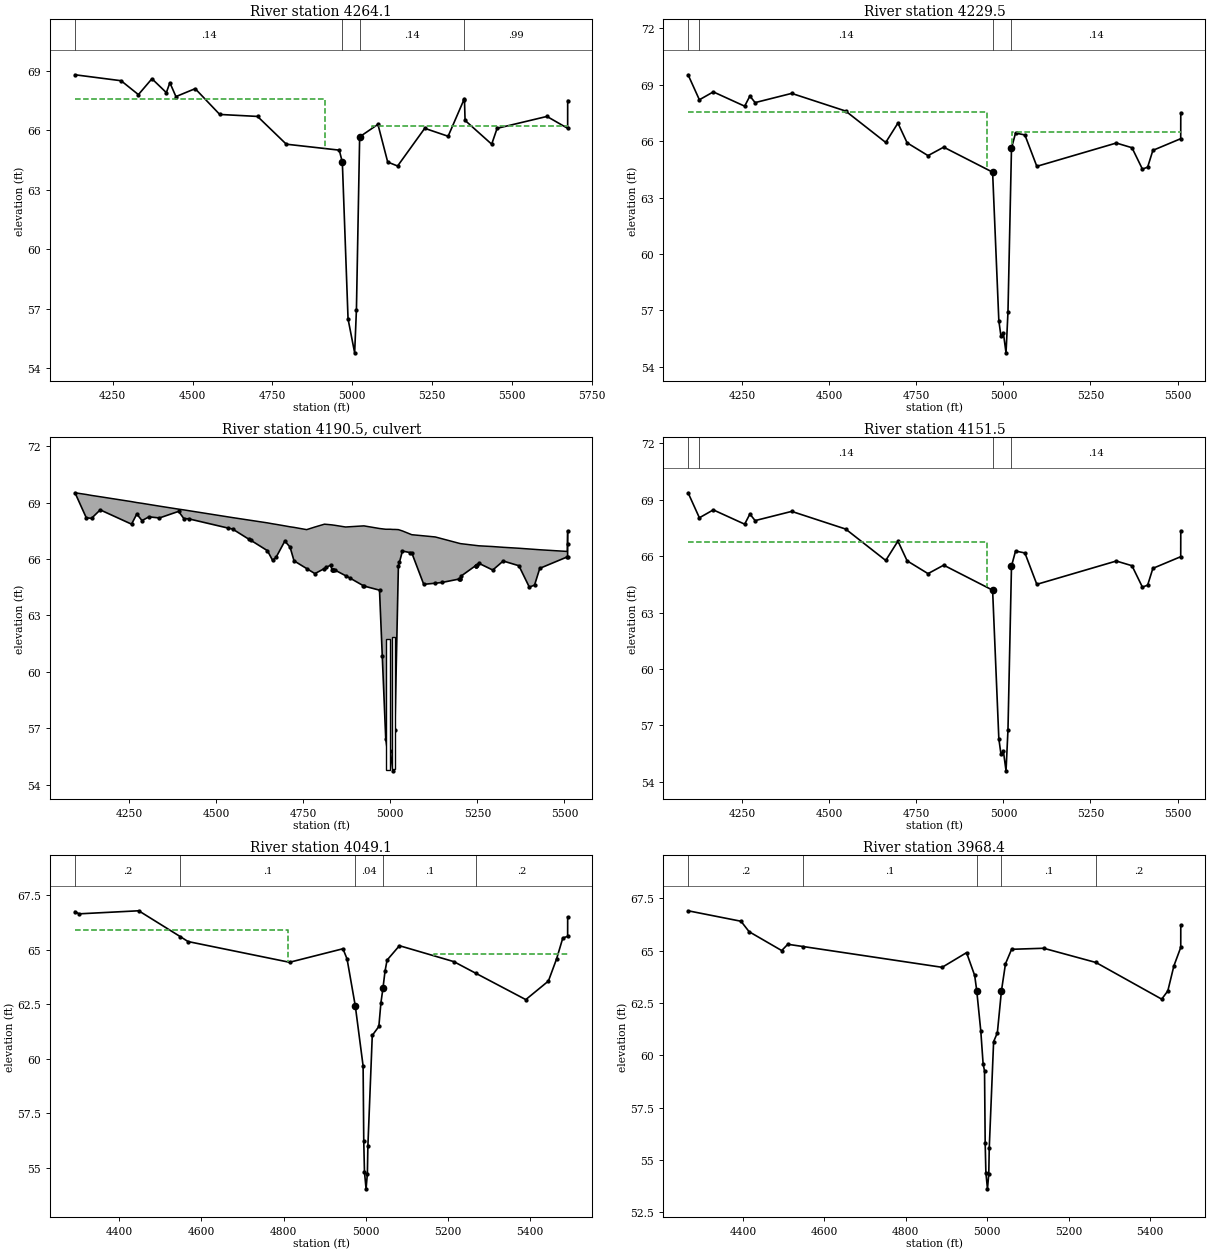
Type RM Length L Ch R = 1 ,4264.1  ,9.4,34.6,57.1
BEGIN DESCRIPTION:
Cross Section 4264.1 - Interpolated
END DESCRIPTION:
XS GIS Cut Line= 6
      3156607.83     13916453.34       3156210.3     13916426.65
      3155741.52     13916406.65      3155619.32      13916431.5
        3155467.     13916477.68      3155123.23     13916663.25
#Sta/Elev= 30
  4132.1    68.8  4276.4    68.5  4330.6    67.8    4373    68.6  4418.1    67.9
  4429.1    68.4  4448.1    67.7  4508.3    68.1  4585.2    66.8  4703.5    66.7
  4793.6    65.3  4959.4      65    4969   64.39 4986.88   56.49 5007.54   54.78
 5013.12   56.96 5023.21   65.67  5080.4    66.3    5111    64.4    5142    64.2
  5226.9    66.1  5300.1    65.7  5349.8   67.55  5351.2    67.6  5353.2    66.5
  5436.5    65.3  5453.5    66.1  5609.5    66.7  5674.3    66.1  5674.4    67.5
#Mann= 4 , 1 , 0
  4132.1     .14       0    4969     .04       0 5023.21     .14       0
  5349.8     .99       0
#XS Ineff= 2 , 0
       0    4915    67.6    5063       0    66.2
Permanent Ineff=
       F       F
Bank Sta=4969,5023.21
XS Rating Curve= 0
Exp/Cntr=.5,.3

Type RM Length L Ch R = 1 ,4229.5  ,78,78,78
BEGIN DESCRIPTION:
Upstream Section of Bridge/Culvert/Weir
END DESCRIPTION:
XS GIS Cut Line= 6
      3156615.05     13916449.25      3156112.25     13916402.22
      3155910.43     13916393.98      3155597.54     13916381.21
      3155484.93     13916376.62      3155203.63      13916365.2
#Sta/Elev= 30
  4094.8   69.53  4127.2    68.2  4167.2   68.62  4257.2   67.86  4272.2    68.4
  4287.2   68.05  4392.2   68.54  4547.2    67.6  4662.2   65.93  4697.2   66.96
  4723.6   65.91  4783.6   65.23  4828.6   65.68    4969   64.35 4986.88   56.45
 4992.78   55.66    5000   55.78 5007.54   54.74 5013.12   56.92 5023.21   65.63
 5034.85   66.43 5061.66   66.33 5095.94   64.66  5324.1    65.9  5369.1   65.65
  5399.1   64.51  5414.1   64.62  5429.1   65.51    5509   66.13  5509.2   67.51
#Mann= 4 , 1 , 0
  4094.8      .2       0  4127.2     .14       0    4969     .04       0
 5023.21     .14       0
#XS Ineff= 2 , 0
       0    4952   67.54    5026       0    66.5
Permanent Ineff=
       F       F
Bank Sta=4969,5023.21
XS Rating Curve= 0
Exp/Cntr=.5,.3

Type RM Length L Ch R = 2 ,4190.5  ,,,
BEGIN DESCRIPTION:
ATASCOCITA ROAD - 35 DEGREE SKEW
Structure ID: P03-2
END DESCRIPTION:
Bridge Culvert--1,0,-1,-1, 0
Deck Dist Width WeirC Skew NumUp NumDn MinLoCord MaxHiCord MaxSubmerge Is_Ogee
10,58,3,0, 50, 50, , , .95, 0, 1,1,,
  4094.8  4127.2  4142.2  4167.2  4257.2  4272.2  4287.2  4307.2  4337.2  4392.2
  4407.2  4547.2  4647.2  4662.2  4672.2  4697.2  4712.2  4723.6  4759.8  4783.6
  4810.9  4828.6 4833.21 4840.92  4871.5 4924.15    4969 4986.88 4992.78    5000
 5007.54 5013.12 5023.21 5034.85 5061.66 5095.94  5129.2 5200.33  5204.1  5254.1
  5294.1  5324.1  5369.1  5399.1  5414.1  5429.1  5508.1    5509  5509.1  5509.2
   69.52   69.43   69.38   69.31   69.05      69   68.96    68.9   68.81   68.65
   68.61    68.2   67.92   67.87   67.84   67.76   67.71   67.68   67.56    67.7
   67.85   67.82   67.81   67.79    67.7   67.76   67.62   67.58   67.58   67.58
   67.57   67.57   67.56   67.49   67.29   67.23   67.17   66.82   66.81    66.7
   66.66   66.62   66.57   66.53   66.51   66.49    66.4   67.39    67.5    67.5
   69.52   68.19   68.16   68.61   67.85   68.39   68.04   68.24   68.18   68.53
   68.15   67.59   66.44   65.92   66.09   66.95   66.63    65.9   65.49   65.22
   65.49   65.67   65.39   65.41   65.11   64.56   64.34   56.44   55.65   55.77
   54.73   56.91   65.62   66.42   66.32   64.65   64.71   64.93    65.1   65.77
   65.41   65.89   65.64    64.5   64.61    65.5   66.11   66.12   66.81    67.5
  4094.8  4127.2  4142.2  4167.2  4257.2  4272.2  4287.2  4307.2  4337.2  4392.2
  4407.2  4547.2  4647.2  4662.2  4672.2  4697.2  4712.2  4723.6  4759.8  4783.6
  4810.9  4828.6 4833.21 4840.92  4871.5 4924.15    4969 4986.88 4992.78    5000
 5007.54 5013.12 5023.21 5034.85 5061.66 5095.94  5129.2 5200.33  5204.1  5254.1
  5294.1  5324.1  5369.1  5399.1  5414.1  5429.1  5508.1    5509  5509.1  5509.2
   69.52   69.43   69.38   69.31   69.05      69   68.96    68.9   68.81   68.65
   68.61    68.2   67.92   67.87   67.84   67.76   67.71   67.68   67.56    67.7
   67.85   67.82   67.81   67.79    67.7   67.76   67.62   67.58   67.58   67.58
   67.57   67.57   67.56   67.49   67.29   67.23   67.17   66.82   66.81    66.7
   66.66   66.62   66.57   66.53   66.51   66.49    66.4   67.39    67.5    67.5
   69.42   68.09   68.06   68.51   67.75   68.29   67.94   68.14   68.08   68.43
   68.05   67.49   66.34   65.82   65.99   66.85   66.53    65.8   65.39   65.12
   65.39   65.57   65.29   65.31   65.01   64.46   64.24   56.34   55.55   55.67
   54.63   56.81   65.52   66.32   66.22   64.55   64.61   64.83      65   65.67
   65.31   65.79   65.54    64.4   64.51    65.4   66.01   66.02   66.71    67.4
BR Coef= 1 , 0 , 0 ,1.25, 0 ,,,.8,-1,2,0,
WSPro=,,,, 1 ,,,, 0 ,,,, 0 ,,,,-1 ,-1 ,-1 , 0 , 0 , 0 , 0 , 0
Culvert=2,7,10,58,.015,.4,1,8,1,54.76,4993.2,54.88,4993.2,Culvert #1  , 0 ,10
Culvert Bottom n=.015
Culvert=2,7,10,58,.015,.4,1,8,1,54.85,5009.2,54.85,5009.2,Culvert #2  , 0 ,10
Culvert Bottom n=.015
BR U #Sta/Elev= 70
  4094.8   69.52  4127.2   68.19  4142.2   68.16  4167.2   68.61  4257.2   67.85
  4272.2   68.39  4287.2   68.04  4307.2   68.24  4337.2   68.18  4392.2   68.53
  4407.2   68.15  4422.2   68.13  4534.8   67.64  4547.2   67.59  4594.8   67.04
  4599.8   66.99  4647.2   66.44  4662.2   65.92  4672.2   66.09  4697.2   66.95
  4712.2   66.63  4723.6    65.9  4759.8   65.49  4783.6   65.22  4810.9   65.49
  4816.1   65.55  4828.6   65.67 4833.21   65.39 4836.09    65.4  4836.2    65.4
 4836.31    65.4 4840.92   65.41  4871.5   65.11 4885.36   64.97  4922.3   64.58
 4924.15   64.56    4969   64.34  4976.9   60.85 4986.88   56.44 4992.78   55.65
    5000   55.77 5007.54   54.73 5013.12   56.91 5023.21   65.62  5026.3   65.83
 5034.85   66.42  5056.3   66.34 5061.66   66.32 5095.94   64.65  5129.2   64.71
 5148.75   64.75  5197.2   64.93 5200.24   64.94 5200.33   64.93  5204.1    65.1
 5244.69   65.64  5244.8   65.65 5244.91   65.65  5248.5   65.69  5254.1   65.77
  5294.1   65.41  5324.1   65.89  5369.1   65.64  5399.1    64.5  5414.1   64.61
  5429.1    65.5  5508.1   66.11    5509   66.12  5509.1   66.81  5509.2    67.5
BR U #Mann= 4
  4094.8      .2  4127.2     .14    4969     .04 5023.21     .14
BR U Banks=4969,5023.21
BR D #Sta/Elev= 70
  4094.8   69.42  4127.2   68.09  4142.2   68.06  4167.2   68.51  4257.2   67.75
  4272.2   68.29  4287.2   67.94  4307.2   68.14  4337.2   68.08  4392.2   68.43
  4407.2   68.05  4422.2   68.03  4534.8   67.54  4547.2   67.49  4594.8   66.94
  4599.8   66.89  4647.2   66.34  4662.2   65.82  4672.2   65.99  4697.2   66.85
  4712.2   66.53  4723.6    65.8  4759.8   65.39  4783.6   65.12  4810.9   65.39
  4816.1   65.45  4828.6   65.57 4833.21   65.29 4836.09    65.3  4836.2    65.3
 4836.31    65.3 4840.92   65.31  4871.5   65.01 4885.36   64.87  4922.3   64.48
 4924.15   64.46    4969   64.24  4976.9   60.75 4986.88   56.34 4992.78   55.55
    5000   55.67 5007.54   54.63 5013.12   56.81 5023.21   65.52  5026.3   65.73
 5034.85   66.32  5056.3   66.24 5061.66   66.22 5095.94   64.55  5129.2   64.61
 5148.75   64.65  5197.2   64.83 5200.24   64.84 5200.33   64.83  5204.1      65
 5244.69   65.54  5244.8   65.55 5244.91   65.55  5248.5   65.59  5254.1   65.67
  5294.1   65.31  5324.1   65.79  5369.1   65.54  5399.1    64.4  5414.1   64.51
  5429.1    65.4  5508.1   66.01    5509   66.02  5509.1   66.71  5509.2    67.4
BR D #Mann= 4
  4094.8      .2  4127.2     .14    4969     .04 5023.21     .14
BR D Banks=4969,5023.21
BC Design=,, 0 ,, 0 ,,,,,,

Type RM Length L Ch R = 1 ,4151.5  ,102.4,102.4,102.4
BEGIN DESCRIPTION:
Downstream Section of Bridge/Culvert/Weir
END DESCRIPTION:
XS GIS Cut Line= 6
      3156576.35     13916381.53      3156073.55      13916334.5
      3155871.73     13916326.26      3155558.84     13916313.49
      3155446.23      13916308.9      3155164.93     13916297.48
#Sta/Elev= 30
  4094.8   69.37  4127.2   68.04  4167.2   68.46  4257.2    67.7  4272.2   68.24
  4287.2   67.89  4392.2   68.38  4547.2   67.44  4662.2   65.77  4697.2    66.8
  4723.6   65.75  4783.6   65.07  4828.6   65.52    4969   64.19 4986.88   56.29
 4992.78    55.5    5000   55.62 5007.54   54.58 5013.12   56.76 5023.21   65.47
 5034.85   66.27 5061.66   66.17 5095.94    64.5  5324.1   65.74  5369.1   65.49
  5399.1   64.35  5414.1   64.46  5429.1   65.35    5509   65.97  5509.2   67.35
#Mann= 4 , 1 , 0
  4094.8      .2       0  4127.2     .14       0    4969     .04       0
 5023.21     .14       0
#XS Ineff= 2 , 0
       0    4952   66.76    5026       0    64.7
Permanent Ineff=
       F       F
Bank Sta=4969,5023.21
XS Rating Curve= 0
Exp/Cntr=.5,.3

Type RM Length L Ch R = 1 ,4049.1  ,99.4,80.7,63.5
BEGIN DESCRIPTION:
Cross Section 4049.1 - Interpolated
END DESCRIPTION:
XS GIS Cut Line= 6
       3156279.4     13915944.45      3155787.96     13916147.63
      3155628.83     13916225.84      3155411.67     13916273.94
      3155325.42     13916287.83      3155145.95     13916285.27
#Sta/Elev= 30
  4292.6   66.74  4302.6   66.64  4447.6   66.78  4548.4    65.6  4567.6   65.37
  4814.4   64.42  4944.4   65.04  4954.4   64.57  4974.4   62.42  4993.4   59.67
    4995   56.21  4996.7   54.82  5000.6   54.04  5003.8   54.74    5005   55.99
  5015.7   61.07  5031.7   61.48  5036.7   62.56  5041.7   63.23  5046.7   64.01
  5051.7   64.52  5081.7   65.18  5214.1   64.45  5267.2   63.92  5389.1   62.71
  5444.1   63.56  5464.1   64.58  5479.1   65.53  5490.9   65.61    5491    66.5
#Mann= 5 , 1 , 0
  4292.6      .2       0  4548.4      .1       0  4974.4     .04       0
  5041.7      .1       0  5267.2      .2       0
#XS Ineff= 2 , 0
       0    4811    65.9    5167       0    64.8
Permanent Ineff=
       F       F
Bank Sta=4974.4,5041.7
XS Rating Curve= 0
Exp/Cntr=.3,.1

Type RM Length L Ch R = 1 ,3968.4  ,232.8,234.2,242.3
BEGIN DESCRIPTION:
Cross Section 3968.4 - Interpolated
END DESCRIPTION:
XS GIS Cut Line= 6
      3156270.05     13915936.17      3155872.59     13915983.19
      3155585.84     13916157.73      3155465.33       13916245.
      3155326.95     13916272.79       3155142.5     13916283.18
#Sta/Elev= 30
    4265    66.9    4395    66.4    4415    65.9    4495      65    4510    65.3
  4548.4   65.19  4889.2    64.2  4949.2    64.9  4969.2   63.81  4974.2   63.09
  4984.2   61.16  4989.9   59.59  4993.4   59.25    4995   55.79  4996.7    54.4
  5000.6   53.62  5003.8   54.32    5005   55.57  5015.7   60.65  5024.9   61.07
  5034.9   63.07  5044.9   64.37  5059.9   65.06  5138.7   65.11  5267.2   64.43
  5428.7   62.68  5443.7   63.07  5458.7   64.27  5475.5   65.15  5475.6    66.2
#Mann= 5 , 1 , 0
    4265      .2       0  4548.4      .1       0  4974.2     .04       0
  5034.9      .1       0  5267.2      .2       0
#XS Ineff= 2 , 0
       0                    5150       0    64.7
Permanent Ineff=
       F       F
Bank Sta=4974.2,5034.9
XS Rating Curve= 0
Exp/Cntr=.3,.1