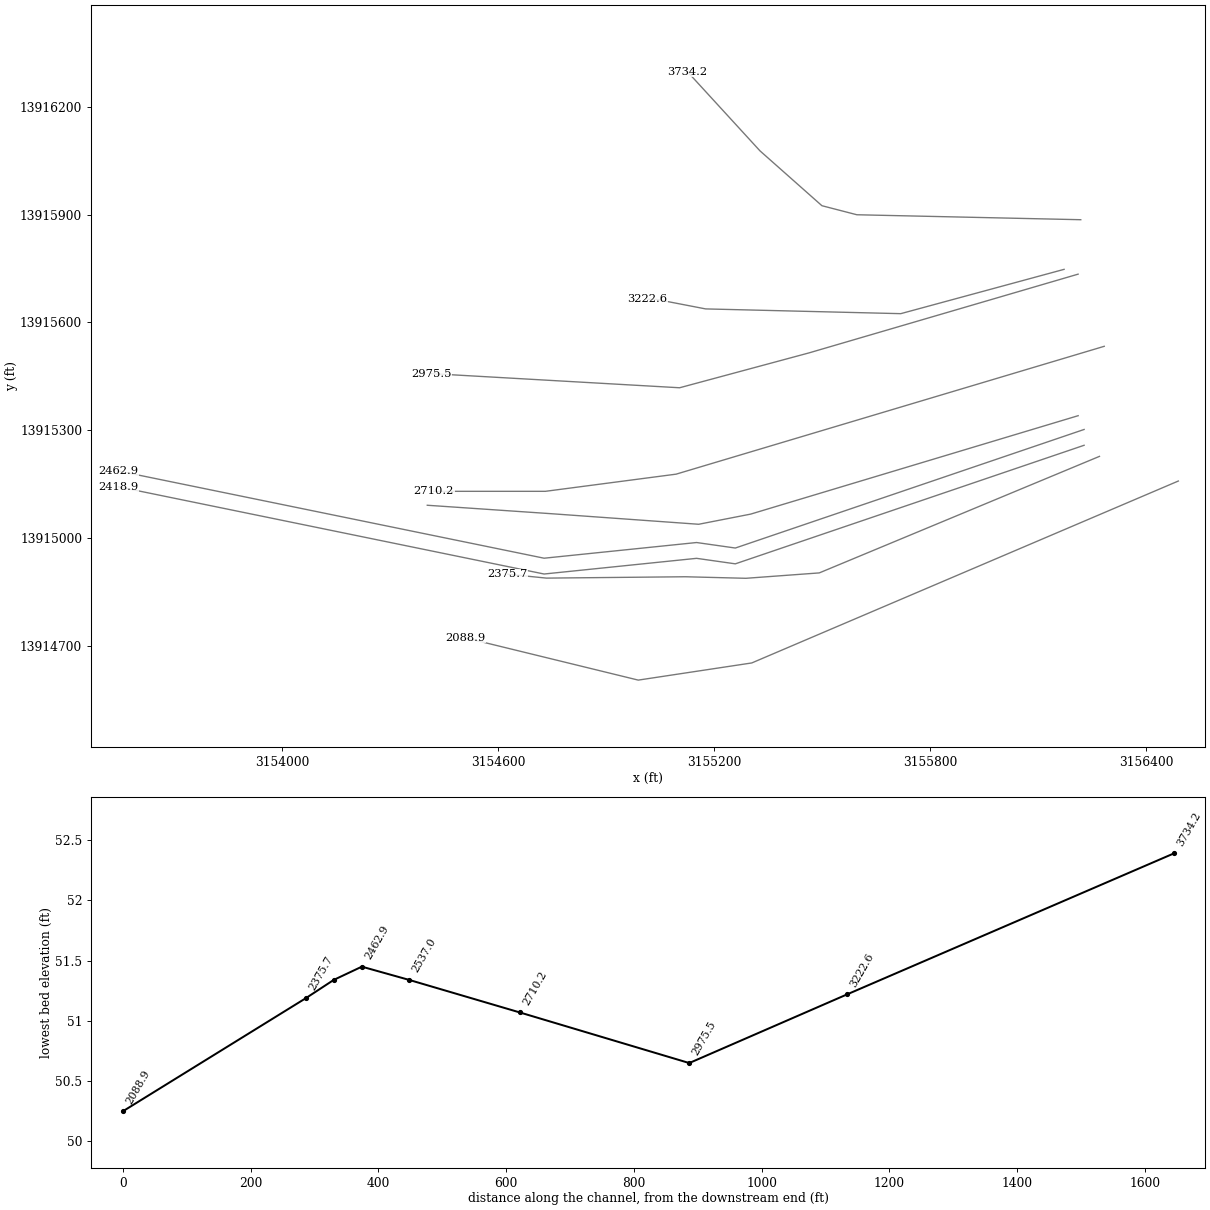
HEC-RAS study P130-03-00.PRJ: P130-03-00

--- P130-03-00.g01 (geometry) --- (continued)

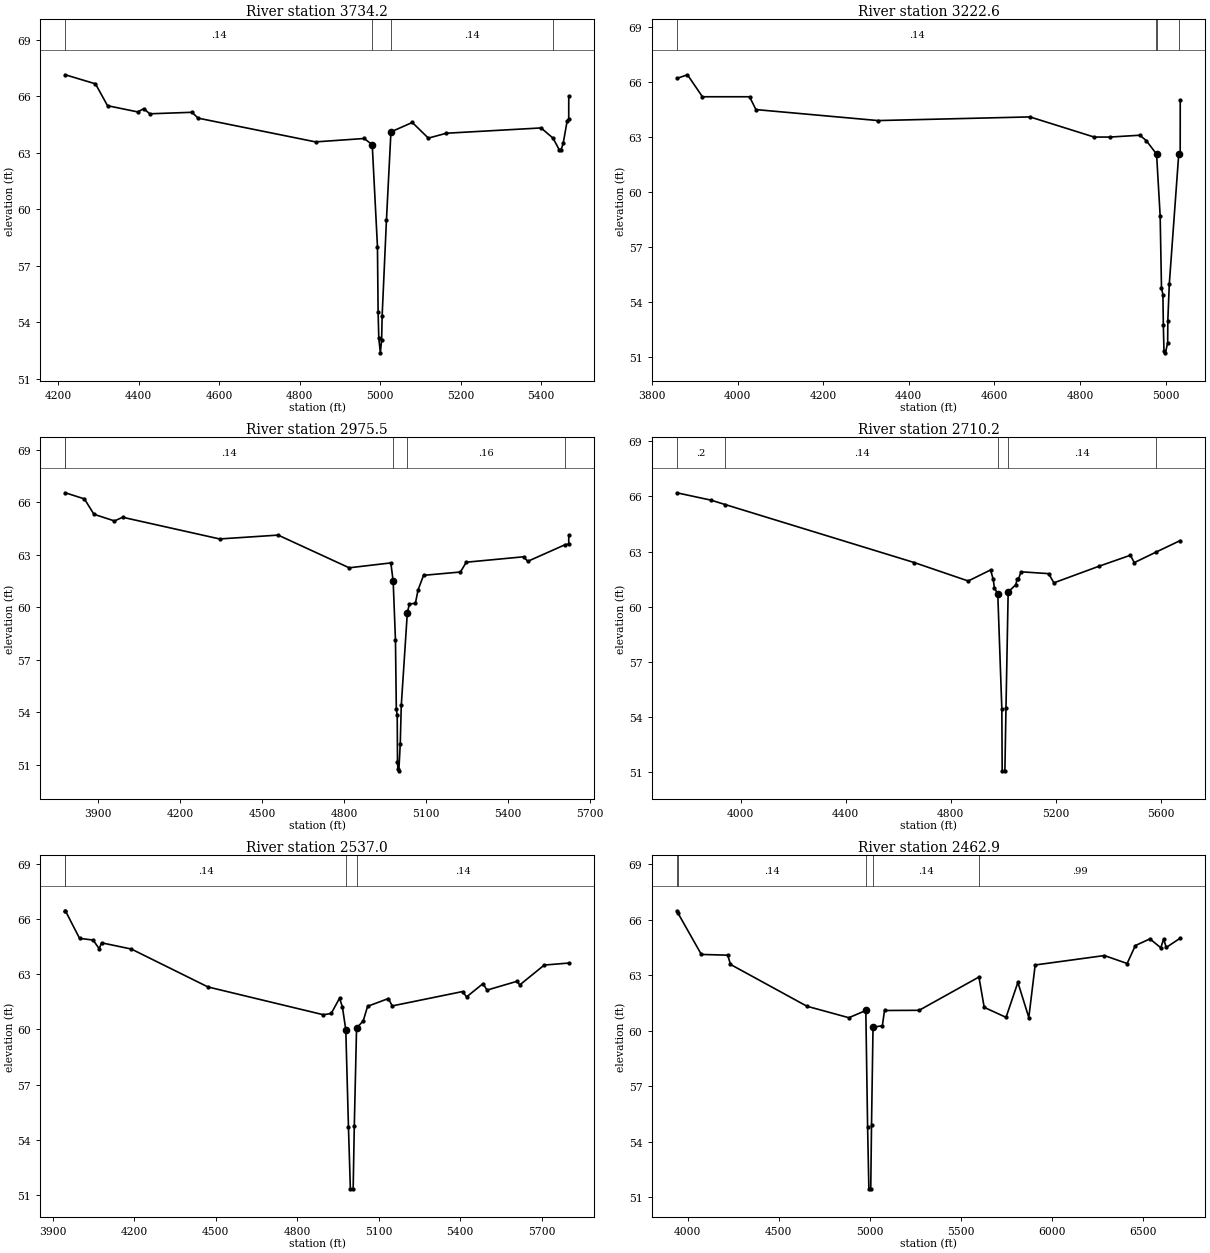
Type RM Length L Ch R = 1 ,3734.2  ,486.7,511.6,793.6
BEGIN DESCRIPTION:
Cross Section 3734.2
END DESCRIPTION:
XS GIS Cut Line= 5
      3156217.57      13915885.7      3155595.69     13915899.51
      3155498.67     13915924.67      3155326.62     13916077.36
      3155124.91     13916297.95
#Sta/Elev= 30
  4217.6   67.14  4292.6   66.66  4322.6    65.5  4397.6   65.17  4412.6   65.34
  4427.6   65.07  4532.6   65.15  4547.6   64.84  4839.6   63.58  4960.5   63.76
  4980.4   63.43  4993.4   58.02    4995   54.56  4996.7   53.17  5000.6   52.39
  5003.8   53.09    5005   54.34  5015.7   59.42  5026.9   64.11  5079.9   64.61
  5119.9   63.78  5164.9   64.04  5399.9   64.32  5429.7   63.78  5444.9   63.17
  5449.9   63.17  5454.9    63.5  5464.9    64.7  5468.7    64.8  5468.8      66
#Mann= 4 , 1 , 0
  4217.6     .14       0  4980.4     .04       0  5026.9     .14       0
  5429.7     .99       0
#XS Ineff= 2 , 0
       0                  5399.9       0   64.32
Permanent Ineff=
       F       F
Bank Sta=4980.4,5026.9
XS Rating Curve= 0
Exp/Cntr=.3,.1

Type RM Length L Ch R = 1 ,3222.6  ,211.5,247.1,253.9
BEGIN DESCRIPTION:
Cross Section 3222.6 - Interpolated
END DESCRIPTION:
XS GIS Cut Line= 5
      3156171.26     13915747.55      3155717.56     13915624.21
      3155175.76     13915637.43      3155039.21     13915663.86
      3155014.17     13915664.34
#Sta/Elev= 25
  3857.9    66.2  3882.9    66.4  3917.9    65.2  4027.9    65.2  4042.9    64.5
  4328.1    63.9  4683.1    64.1  4833.1      63    4870      63    4940    63.1
    4955    62.8  4978.2   62.09  4978.9   62.07  4987.3   58.69  4990.4   54.75
  4993.7    54.4  4994.7   52.73  4996.2   51.32  4999.6   51.22  5004.8   51.76
  5005.2   52.98  5008.6   54.97  5030.7   62.07  5034.1    62.1  5034.2      65
#Mann= 4 , 1 , 0
  3857.9     .14       0  4978.2     .14       0  4978.9     .04       0
  5030.7     .99       0
Bank Sta=4978.9,5030.7
XS Rating Curve= 0
Exp/Cntr=.3,.1

Type RM Length L Ch R = 1 ,2975.5  ,229.9,265.3,310.8
BEGIN DESCRIPTION:
Cross Section 2975.5
END DESCRIPTION:
XS GIS Cut Line= 4
      3156210.21      13915734.2      3155462.73     13915514.99
      3155103.36     13915417.96      3154413.05      13915457.4
#Sta/Elev= 30
  3778.9   66.55  3848.9    66.2  3883.9   65.32  3958.9   64.94  3988.9   65.15
  4343.9   63.91  4557.9   64.13  4817.9   62.26  4970.3   62.54  4978.9    61.5
  4987.3   58.12  4990.4   54.18  4993.7   53.83  4994.7   51.16  4996.2   50.75
  4999.6   50.65  5004.8   52.19  5008.6    54.4  5030.7   59.69  5038.4    60.2
  5060.1   60.22  5070.1      61  5090.1   61.83  5225.1   62.02  5246.4   62.58
  5456.4   62.89  5471.4   62.63    5608   63.58  5621.4   63.62  5621.5   64.12
#Mann= 5 , 1 , 0
  3778.9      .2       0  3778.9     .14       0  4978.9     .04       0
  5030.7     .16       0    5608     .99       0
Bank Sta=4978.9,5030.7
XS Rating Curve= 0
Exp/Cntr=.3,.1

Type RM Length L Ch R = 1 ,2710.2  ,263.8,173.2,170.6
BEGIN DESCRIPTION:
Cross Section 2710.2 - Interpolated
END DESCRIPTION:
XS GIS Cut Line= 4
       3156282.8     13915533.35      3155093.67     13915177.48
      3154730.62     13915129.71      3154420.64     13915129.71
#Sta/Elev= 25
  3756.2    66.2  3886.2    65.8  3940.5   65.56  4661.2    62.4  4866.2    61.4
  4951.2      62  4961.2    61.5  4966.2      61  4978.7   60.71  4994.2   54.43
  4995.5   51.07  5005.8   51.07    5010    54.5  5018.3    60.8  5047.4    61.2
  5052.4    61.5  5057.4    61.5  5067.4    61.9  5172.4    61.8  5192.4    61.3
  5363.6    62.2  5483.6    62.8  5498.6    62.4  5582.6   62.98  5673.6    63.6
#Mann= 5 , 1 , 0
  3756.2      .2       0  3940.5     .14       0  4978.7     .04       0
  5018.3     .14       0  5582.6      .2       0
Bank Sta=4978.7,5018.3
XS Rating Curve= 0
Exp/Cntr=.3,.1

Type RM Length L Ch R = 1 ,2537.0  ,77.9,74.1,73.8
BEGIN DESCRIPTION:
Cross Section 2537.0 - Interpolated
END DESCRIPTION:
XS GIS Cut Line= 5
      3156210.35     13915340.23      3155300.76     13915066.28
      3155156.36       13915038.      3154747.21     13915067.39
      3154402.56     13915090.93
#Sta/Elev= 30
  3946.4   66.45  3946.8   66.45    3999   64.95  4048.6   64.86  4071.3   64.39
  4079.9   64.71  4189.6   64.37  4471.6   62.31  4896.3    60.8  4925.1   60.87
  4955.7    61.7  4966.3   61.22  4978.7   59.98  4988.5    54.7  4995.5   51.34
  5005.8   51.34    5010   54.77  5018.3   60.07  5042.9   60.47    5059   61.26
  5135.5   61.68  5149.5   61.28  5408.3   62.06  5423.3   61.77  5483.5   62.49
  5498.5   62.14  5609.3   62.62  5618.8   62.42    5709    63.5  5799.2   63.61
#Mann= 4 , 1 , 0
  3946.4      .2       0  3946.8     .14       0  4978.7    .035       0
  5018.3     .14       0
Bank Sta=4978.7,5018.3
XS Rating Curve= 0
Exp/Cntr=.5,.3

Type RM Length L Ch R = 1 ,2462.9  ,44,44,44
BEGIN DESCRIPTION:
Upstream Section of Bridge/Culvert/Weir
END DESCRIPTION:
XS GIS Cut Line= 5
      3156226.85     13915301.87      3155258.15     13914971.87
      3155150.49     13914987.19      3154727.02     13914943.55
      3153544.99     13915186.32
#Sta/Elev= 30
  3940.5   66.48  3946.8   66.36  4075.5   64.12  4220.5   64.08  4235.5   63.58
  4655.5   61.32  4885.5    60.7  4978.7   61.09  4988.5   54.81  4995.5   51.45
  5005.8   51.45    5010   54.88  5018.3   60.18  5069.6   60.27  5081.4   61.09
  5271.5    61.1    5600    62.9  5628.8   61.26  5748.8   60.72  5813.8   62.61
  5873.8   60.71  5908.8   63.55  6288.8   64.06  6413.8   63.63  6458.8    64.6
  6538.8   64.96  6598.8   64.48  6613.8   64.95  6628.8    64.5  6705.4      65
#Mann= 5 , 1 , 0
  3940.5      .2       0  3946.8     .14       0  4978.7    .035       0
  5018.3     .14       0    5600     .99       0
#XS Ineff= 2 , 0
       0    4967      60    5492       0      62
Permanent Ineff=
       F       F
Bank Sta=4978.7,5018.3
XS Rating Curve= 0
Exp/Cntr=.5,.3

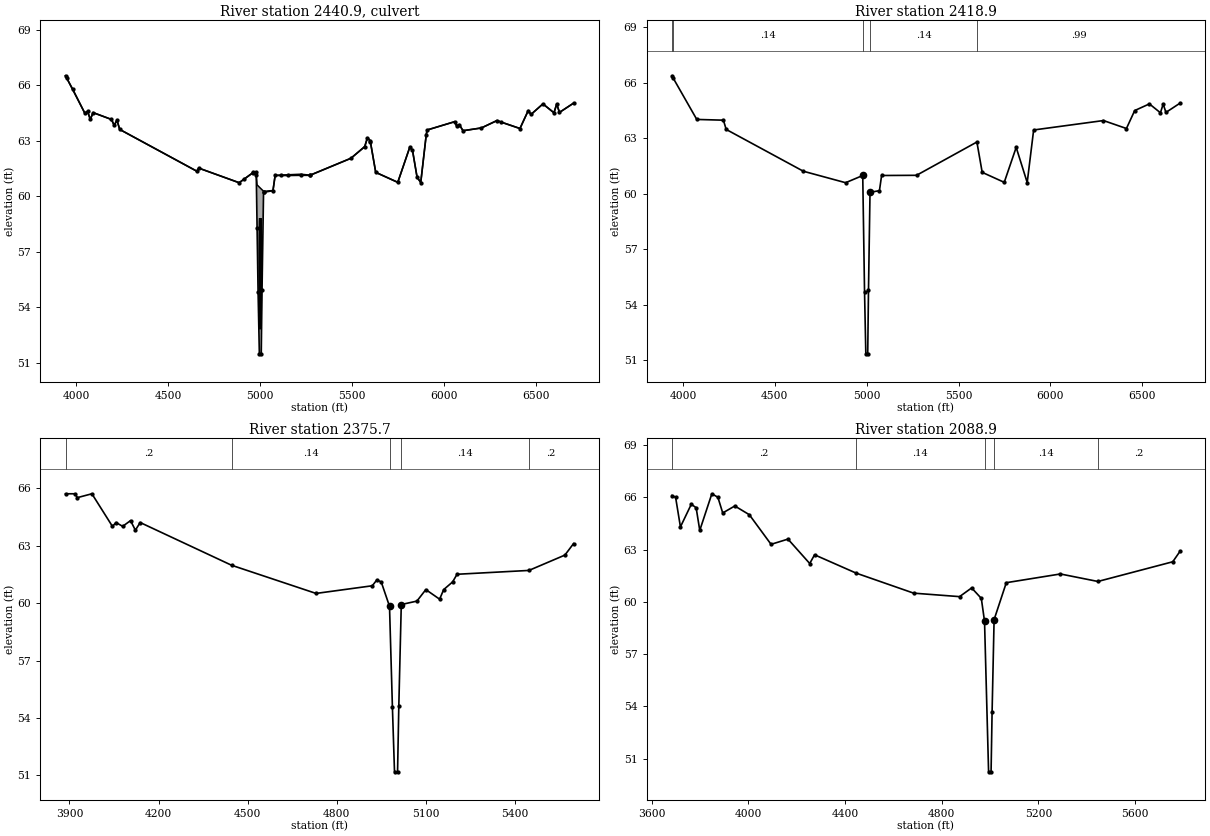
Type RM Length L Ch R = 2 ,2440.9  ,,,
BEGIN DESCRIPTION:
DIRT ROAD D/S OF ATASCOCITA ROAD
Structure ID: P03-1
END DESCRIPTION:
Bridge Culvert--1,0,-1,-1, 0
Deck Dist Width WeirC Skew NumUp NumDn MinLoCord MaxHiCord MaxSubmerge Is_Ogee
10,24,3,0, 52, 52, , , .95, 0, 1,1,,
  3940.5  4045.5  4060.5  4075.5  4090.5  4190.5  4205.5  4220.5  4235.5  4655.5
  4665.5  4885.5  4963.5  4975.5  4978.7  4983.1  4988.5  4995.5  5005.8    5010
  5018.3  5018.9  5069.6  5081.4  5221.7  5271.5  5493.8  5568.8  5583.8  5598.8
  5628.8  5748.8  5813.8  5828.8  5853.8  5873.8  5903.8  5908.8  6058.8  6068.8
  6083.8  6103.8  6203.8  6288.8  6413.8  6458.8  6473.8  6538.8  6598.8  6613.8
  6628.8  6705.4
    66.5   64.48   64.58   64.14   64.51   64.14   63.82    64.1    63.6   61.34
   61.51   60.72   61.29   61.31   61.12    60.6   60.55   60.48   60.38   60.34
   60.26   60.25    60.3   61.12   61.18   61.13   62.04   62.67   63.15   62.99
   61.28   60.74   62.63   62.48   61.02   60.73   63.32   63.57   64.02   63.79
   63.86   63.53   63.68   64.08   63.65   64.62   64.41   64.98    64.5   64.97
   64.52   65.02
    66.5   64.48   64.58   64.14   64.51   64.14   63.82    64.1    63.6   61.34
   61.51   60.72   61.28    61.3   61.11   58.29   54.83   51.47   51.47    54.9
    60.2    60.2   60.29   61.11   61.12   61.12   62.04   62.67   63.15   62.99
   61.28   60.74   62.63   62.48   61.02   60.73   63.32   63.57   64.02   63.79
   63.86   63.53   63.68   64.08   63.65   64.62   64.41   64.98    64.5   64.97
   64.52   65.02
  3940.5  4045.5  4060.5  4075.5  4090.5  4190.5  4205.5  4220.5  4235.5  4655.5
  4665.5  4885.5  4963.5  4975.5  4978.7  4983.1  4988.5  4995.5  5005.8    5010
  5018.3  5018.9  5069.6  5081.4  5221.7  5271.5  5493.8  5568.8  5583.8  5598.8
  5628.8  5748.8  5813.8  5828.8  5853.8  5873.8  5903.8  5908.8  6058.8  6068.8
  6083.8  6103.8  6203.8  6288.8  6413.8  6458.8  6473.8  6538.8  6598.8  6613.8
  6628.8  6705.4
    66.5   64.48   64.58   64.14   64.51   64.14   63.82    64.1    63.6   61.34
   61.51   60.72   61.29   61.31   61.12    60.6   60.55   60.48   60.38   60.34
   60.26   60.25    60.3   61.12   61.18   61.13   62.04   62.67   63.15   62.99
   61.28   60.74   62.63   62.48   61.02   60.73   63.32   63.57   64.02   63.79
   63.86   63.53   63.68   64.08   63.65   64.62   64.41   64.98    64.5   64.97
   64.52   65.02
    66.4   64.38   64.48   64.04   64.41   64.04   63.72      64    63.5   61.24
   61.41   60.62   61.18    61.2   61.01   58.19   54.73   51.37   51.37    54.8
    60.1    60.1   60.19   61.01   61.02   61.02   61.94   62.57   63.05   62.89
   61.18   60.64   62.53   62.38   60.92   60.63   63.22   63.47   63.92   63.69
   63.76   63.43   63.58   63.98   63.55   64.52   64.31   64.88    64.4   64.87
   64.42   64.92
BR Coef= 1 , 0 , 0 ,1.25, 0 ,,,.8,-1,2,0,
WSPro=,,,, 1 ,,,, 0 ,,,, 0 ,,,,-1 ,-1 ,-1 , 0 , 0 , 0 , 0 , 0
Culvert=1,6,,24,.015,.2,1,1,3,52.8,4996.6,52.5,4996.6,Culvert #1  , 0 ,10
Culvert Bottom n=.015
Culvert=1,6,,24,.015,.2,1,1,3,52.8,5004,52.5,5004,Culvert #2  , 0 ,10
Culvert Bottom n=.015
BR U #Sta/Elev= 61
  3940.5    66.5  3946.8   66.38  3980.5   65.76  4045.5   64.48  4060.5   64.58
  4075.5   64.14  4090.5   64.51  4190.5   64.14  4205.5   63.82  4220.5    64.1
  4235.5    63.6  4655.5   61.34  4665.5   61.51  4885.5   60.72  4913.8   60.92
  4959.5   61.25  4963.5   61.28  4975.5    61.3  4978.7   61.11  4983.1   58.29
  4988.5   54.83  4995.5   51.47  5005.8   51.47    5010    54.9  5018.3    60.2
  5018.9    60.2  5069.6   60.29  5081.4   61.11    5111   61.11  5151.3   61.11
  5221.7   61.12  5271.4   61.12  5271.5   61.12  5493.8   62.04  5568.8   62.67
  5583.8   63.15  5598.8   62.99    5600   62.92  5628.8   61.28  5748.8   60.74
  5813.8   62.63  5828.8   62.48  5853.8   61.02  5873.8   60.73  5903.8   63.32
  5908.8   63.57  6058.8   64.02  6068.8   63.79  6083.8   63.86  6103.8   63.53
  6203.8   63.68  6288.8   64.08  6308.8      64  6413.8   63.65  6458.8   64.62
  6473.8   64.41  6538.8   64.98  6598.8    64.5  6613.8   64.97  6628.8   64.52
  6705.4   65.02
BR U #Mann= 5
  3940.5      .2  3946.8     .14  4978.7    .035  5018.3     .14    5600     .99
BR U Banks=4978.7,5018.3
BR D #Sta/Elev= 61
  3940.5    66.4  3946.8   66.28  3980.5   65.66  4045.5   64.38  4060.5   64.48
  4075.5   64.04  4090.5   64.41  4190.5   64.04  4205.5   63.72  4220.5      64
  4235.5    63.5  4655.5   61.24  4665.5   61.41  4885.5   60.62  4913.8   60.82
  4959.5   61.15  4963.5   61.18  4975.5    61.2  4978.7   61.01  4983.1   58.19
  4988.5   54.73  4995.5   51.37  5005.8   51.37    5010    54.8  5018.3    60.1
  5018.9    60.1  5069.6   60.19  5081.4   61.01    5111   61.01  5151.3   61.01
  5221.7   61.02  5271.4   61.02  5271.5   61.02  5493.8   61.94  5568.8   62.57
  5583.8   63.05  5598.8   62.89    5600   62.82  5628.8   61.18  5748.8   60.64
  5813.8   62.53  5828.8   62.38  5853.8   60.92  5873.8   60.63  5903.8   63.22
  5908.8   63.47  6058.8   63.92  6068.8   63.69  6083.8   63.76  6103.8   63.43
  6203.8   63.58  6288.8   63.98  6308.8    63.9  6413.8   63.55  6458.8   64.52
  6473.8   64.31  6538.8   64.88  6598.8    64.4  6613.8   64.87  6628.8   64.42
  6705.4   64.92
BR D #Mann= 5
  3940.5      .2  3946.8     .14  4978.7    .035  5018.3     .14    5600     .99
BR D Banks=4978.7,5018.3
BC Design=,, 0 ,, 0 ,,,,,,

Type RM Length L Ch R = 1 ,2418.9  ,43.2,43.2,43.2
BEGIN DESCRIPTION:
Downstream Section of Bridge/Culvert/Weir
END DESCRIPTION:
XS GIS Cut Line= 5
      3156226.85     13915257.87      3155258.15     13914927.87
      3155150.49     13914943.19      3154727.02     13914899.55
      3153544.99     13915142.32
#Sta/Elev= 30
  3940.5   66.37  3946.8   66.25  4075.5   64.01  4220.5   63.97  4235.5   63.47
  4655.5   61.21  4885.5   60.59  4978.7   60.98  4988.5    54.7  4995.5   51.34
  5005.8   51.34    5010   54.77  5018.3   60.07  5069.6   60.16  5081.4   60.98
  5271.5   60.99    5600   62.79  5628.8   61.15  5748.8   60.61  5813.8    62.5
  5873.8    60.6  5908.8   63.44  6288.8   63.95  6413.8   63.52  6458.8   64.49
  6538.8   64.85  6598.8   64.37  6613.8   64.84  6628.8   64.39  6705.4   64.89
#Mann= 5 , 1 , 0
  3940.5      .2       0  3946.8     .14       0  4978.7    .035       0
  5018.3     .14       0    5600     .99       0
#XS Ineff= 2 , 0
       0    4967    59.5    5492       0      62
Permanent Ineff=
       F       F
Bank Sta=4978.7,5018.3
XS Rating Curve= 0
Exp/Cntr=.5,.3

Type RM Length L Ch R = 1 ,2375.7  ,186.6,286.8,295.7
BEGIN DESCRIPTION:
Cross Section 2375.7 - Interpolated
END DESCRIPTION:
XS GIS Cut Line= 6
      3156269.49     13915226.99       3155491.3     13914902.63
      3155287.49     13914887.62      3155119.48     13914891.91
      3154733.55     13914888.15      3154625.97     13914899.01
#Sta/Elev= 30
  3886.9    65.7  3918.6    65.7    3927    65.5  3975.7    65.7  4044.8      64
    4057    64.2  4079.2      64  4105.7    64.3    4122    63.8  4138.2    64.2
  4445.8   61.97    4730    60.5  4919.3    60.9  4934.3    61.2  4949.3    61.1
  4977.2   59.83    4987   54.55    4994   51.19  5004.3   51.19  5008.5   54.62
  5016.8   59.92  5069.4    60.1  5099.4    60.7  5145.8    60.2  5159.5    60.7
  5189.5    61.1  5204.5    61.5  5446.3    61.7  5567.3    62.5  5596.5    63.1
#Mann= 5 , 1 , 0
  3886.9      .2       0  4445.8     .14       0  4977.2     .04       0
  5016.8     .14       0  5446.3      .2       0
Bank Sta=4977.2,5016.8
XS Rating Curve= 0
Exp/Cntr=.3,.1

Type RM Length L Ch R = 1 ,2088.9  ,360.7,393,562.8
BEGIN DESCRIPTION:
Cross Section 2088.9 - Interpolated
END DESCRIPTION:
XS GIS Cut Line= 4
      3156488.53     13915158.37      3155303.85     13914652.02
      3154988.57     13914604.25      3154507.81     13914721.99
#Sta/Elev= 30
  3683.9    66.1  3698.9      66  3718.9    64.3  3763.9    65.6  3783.9    65.4
  3798.9    64.1  3848.9    66.2  3873.9      66  3893.9    65.1  3943.9    65.5
  4003.9      65  4093.9    63.3  4163.9    63.6  4253.9    62.2  4273.9    62.7
  4445.8   61.65  4683.9    60.5  4873.9    60.3  4923.9    60.8  4963.9    60.2
  4977.2   58.89    4994   50.25  5004.3   50.25  5008.5   53.68  5016.8   58.98
  5067.3    61.1  5291.1    61.6  5446.3   61.17  5756.1    62.3  5786.1    62.9
#Mann= 5 , 1 , 0
  3683.9      .2       0  4445.8     .14       0  4977.2     .04       0
  5016.8     .14       0  5446.3      .2       0
#XS Ineff= 2 , 0
       0                  5291.1       0    61.6
Permanent Ineff=
       F       F
Bank Sta=4977.2,5016.8
XS Rating Curve= 0
Exp/Cntr=.3,.1