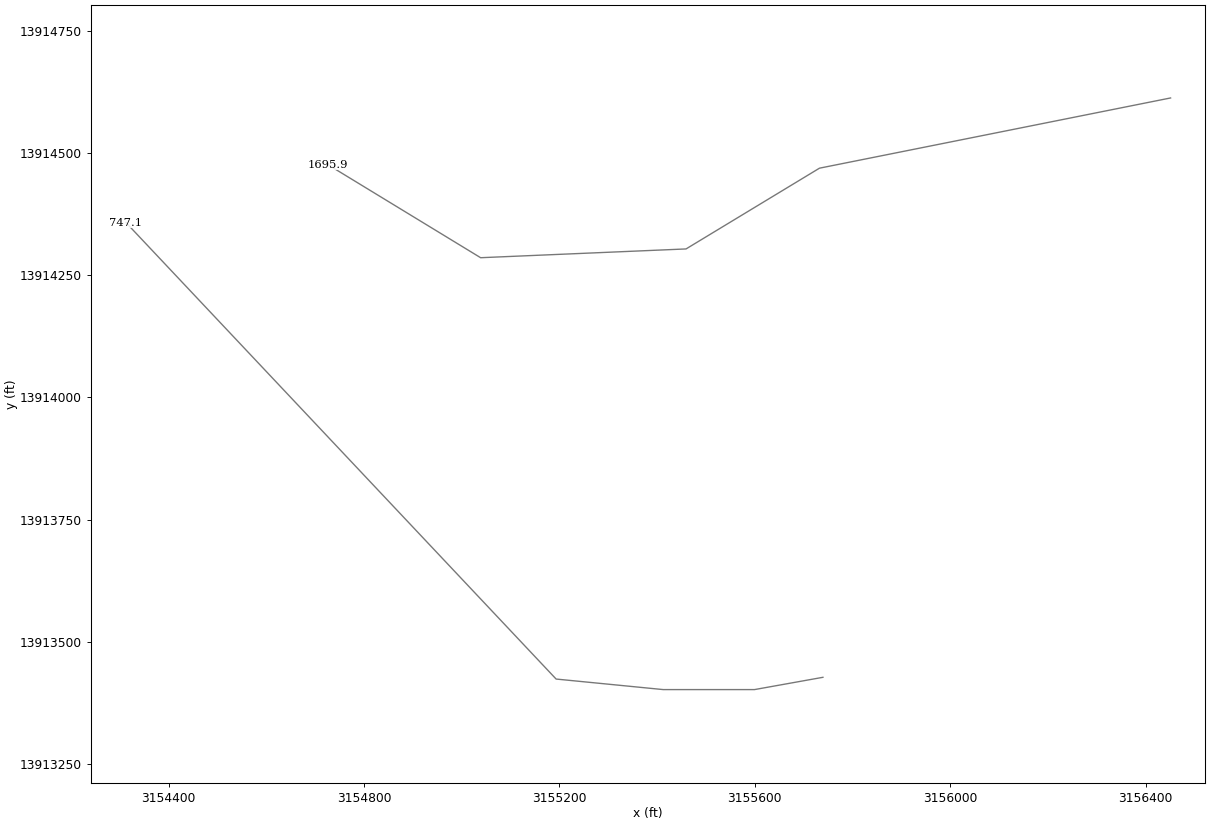
HEC-RAS study P130-03-00.PRJ: P130-03-00

--- P130-03-00.g01 (geometry) --- (continued)

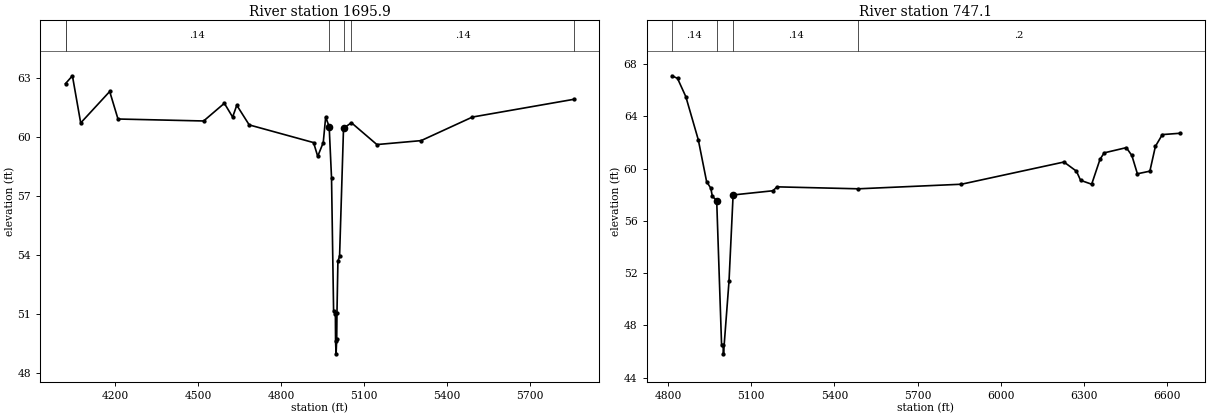
Type RM Length L Ch R = 1 ,1695.9  ,984.1,948.8,911.6
BEGIN DESCRIPTION:
Cross Section 1695.9
END DESCRIPTION:
XS GIS Cut Line= 5
      3156450.98     13914612.99      3155732.25     13914469.24
      3155459.14     13914303.93      3155038.68     13914285.96
      3154726.03     13914476.43
#Sta/Elev= 30
  4020.2    62.7  4045.2    63.1  4075.2    60.7  4180.2    62.3  4210.2    60.9
  4520.2    60.8  4595.2    61.7  4625.2      61  4640.2    61.6  4685.2    60.6
  4918.2    59.7  4933.2      59  4953.2    59.7    4962      61  4974.7   60.51
  4983.2    57.9  4990.7   51.12  4997.1   50.97  4997.8   49.59  4999.7   48.95
    5002   49.72  5002.9   51.04  5006.3   53.66  5012.3   53.91  5026.6   60.43
  5055.2   60.71  5147.4    59.6  5307.4    59.8  5493.3      61  5859.3    61.9
#Mann= 6 , 1 , 0
  4020.2      .2       0  4020.2     .14       0  4974.7     .04       0
  5026.6     .14       0  5055.2     .14       0  5859.3      .2       0
Bank Sta=4974.7,5026.6
XS Rating Curve= 0
Exp/Cntr=.3,.1

Type RM Length L Ch R = 1 ,747.1   ,0,0,0
BEGIN DESCRIPTION:
Cross Section 747.1
END DESCRIPTION:
XS GIS Cut Line= 5
      3155739.38     13913427.07      3155599.29     13913401.93
      3155412.42     13913401.93      3155193.21     13913423.49
      3154312.76     13914357.84
#Sta/Elev= 30
  4813.8    67.1  4833.8    66.9  4863.8    65.5  4908.8    62.2  4938.8      59
  4953.8    58.5  4959.6   57.87  4975.2   57.55  4992.8    46.5    4998   46.49
  4999.7   45.82  5019.7    51.4  5034.4   57.98    5178    58.3    5193    58.6
  5486.1   58.45  5858.3    58.8  6228.3    60.5  6273.3    59.8  6288.3    59.1
  6328.3    58.8  6358.3    60.7  6373.3    61.2  6453.3    61.6  6473.3      61
  6493.3    59.6  6538.3    59.8  6558.3    61.7  6583.3    62.6  6647.1    62.7
#Mann= 4 , 1 , 0
  4813.8     .14       0  4975.2     .04       0  5034.4     .14       0
  5486.1      .2       0
Bank Sta=4975.2,5034.4
XS Rating Curve= 0
Exp/Cntr=.3,.1

Chan Stop Cuts=-1